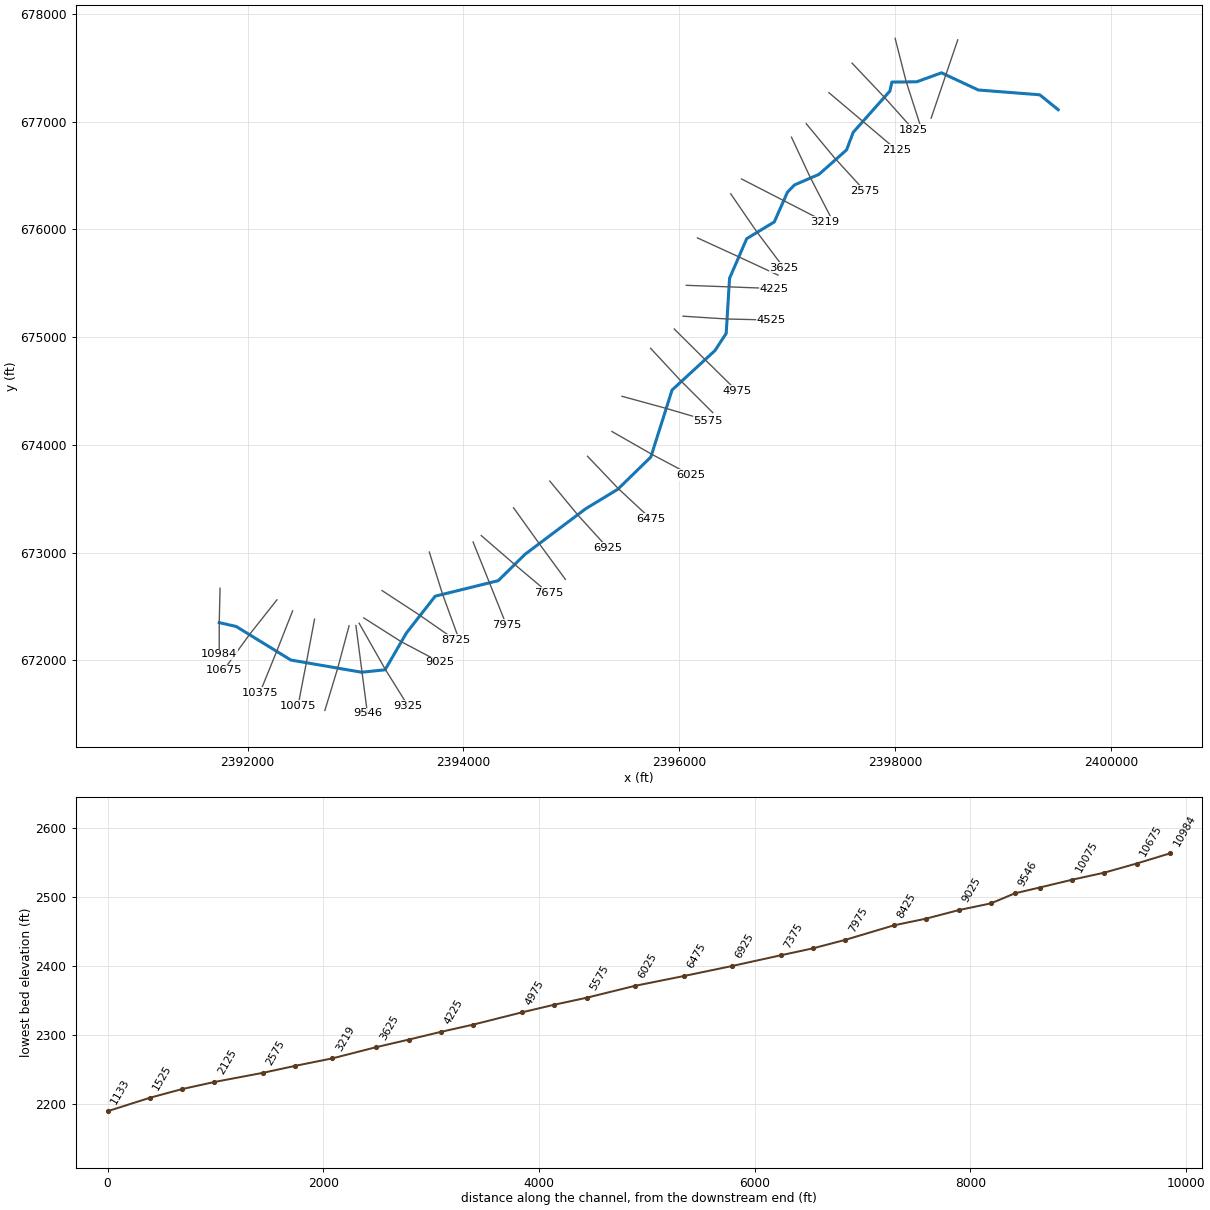
--- WHITESRN.prj (project) ---

Proj Title=WHITESRN
Current Plan=p01
Default Exp/Contr=0,0
English Units
Geom File=g01
Flow File=f01
Plan File=p01
BEGIN DESCRIPTION:
Stream Name: Whites Run
Flood Zone: Approximate
Pendleton County, West Virginia
HEC-RAS Version: 5.0.7
Hydrology Method:
Regression equation
END DESCRIPTION:
DSS Export Rating Curves= 0
DSS Export Rating Curve Sorted= 0
DSS Export Volume Flow Curves= 0
DXF OffsetX= 0
DXF OffsetY= 0
DXF ScaleX= 0
DXF ScaleY= 0

--- WHITESRN.p01 (plan) ---

Plan Title=Floodplain
Program Version=5.07
Short Identifier=Floodplain
Geom File=g01
Flow File=f01
Subcritical Flow
K Sum by GR= 0
Std Step Tol= 0.01
Critical Tol= 0.01
Num of Std Step Trials= 20
Max Error Tol= 0.3
Flow Tol Ratio= 0.001
Split Flow NTrial= 30
Split Flow Tol= 0.02
Split Flow Ratio= 0.02
Log Output Level= 0
Friction Slope Method= 1
Unsteady Friction Slope Method= 2
Unsteady Bridges Friction Slope Method= 1
Parabolic Critical Depth
Global Vel Dist= 0 , 0 , 0
Global Log Level= 0
CheckData=True
Encroach Param=-1 ,0,0, 0
Mapping Interval=1HOUR
Computation Time Step Use Courant=        0
Computation Time Step Use Time Series=    0
Computation Time Step Count To Double=0
Computation Time Step Max Doubling=0
Computation Time Step Max Halving=0
Computation Time Step Residence Courant=0
Run HTab= 0
Run UNet= 0
Run Sediment= 0
Run PostProcess= 0
Run WQNet= 0
Run RASMapper= 0
UNET Theta= 0
UNET Theta Warmup= 0
UNET ZTol= 0
UNET ZSATol= 0
UNET MxIter= 0
UNET Max Iter WO Improvement= 0
UNET MaxInSteps= 0
UNET DtIC= 0
UNET DtMin= 0
UNET MaxCRTS= 0
UNET WFStab= 0
UNET SFStab= 0
UNET WFX= 1
UNET SFX= 1
UNET 1D Methodology=Finite Difference
UNET DSS MLevel= 1
UNET Pardiso=0
UNET DZMax Abort= 0
UNET Use Existing IB Tables= 0
UNET Froude Reduction=False
UNET Froude Limit= 0
UNET Froude Power= 0
UNET D1 Cores= 0
UNET D2 Coriolis=0
UNET D2 Cores= 0
UNET D2 Theta= 1
UNET D2 Theta Warmup= 1
UNET D2 Z Tol= 0.01
UNET D2 Volume Tol= 0.01
UNET D2 Max Iterations= 20
UNET D2 Equation= 0
UNET D2 RampUpFraction=0.1
UNET D2 TimeSlices= 1
UNET D2 BCVolumeCheck=0
UNET D1D2 MaxIter= 0
UNET D1D2 ZTol=0.01
UNET D1D2 QTol=0.1
UNET D1D2 MinQTol=1
Write IC File= 0
Write IC File at Fixed DateTime=0
Write IC File at Sim End=0
Echo Input=False
Echo Parameters=False
Echo Output=False
Write Detailed= 0
HDF Write Warmup=0
HDF Write Time Slices=0
HDF Flush=0
HDF Face Node Velocities=0
HDF Compression= 1
HDF Chunk Size= 1
HDF Spatial Parts= 1
HDF Use Max Rows=0
HDF Fixed Rows= 1
Calibration Method= 0
Calibration Iterations= 20
Calibration Max Change=0.05
Calibration Tolerance=0.2
Calibration Maximum=1.5
Calibration Minimum=0.5
Calibration Optimization Method= 1
WQ AD Non Conservative
WQ ULTIMATE=-1
WQ Max Comp Step=1HOUR
WQ Output Interval=15MIN
WQ Output Selected Increments= 0
WQ Output face flow=0
WQ Output face velocity=0
WQ Output face area=0
WQ Output face dispersion=0
WQ Output cell volume=0
WQ Output cell surface area=0
WQ Output cell continuity=0
WQ Output cumulative cell continuity=0
WQ Output face conc=0
WQ Output face dconc_dx=0
WQ Output face courant=0
WQ Output face peclet=0
WQ Output face adv mass=0
WQ Output face disp mass=0
WQ Output cell mass=0
WQ Output cell source sink temp=0
WQ Output nsm pathways=0
WQ Output nsm derived pathways=0
WQ Output MaxMinRange=-1
WQ Daily Max Min Mean=-1
WQ Daily Range=0
WQ Daily Time=0
WQ Create Restart=0
WQ Fixed Restart=0
WQ System Summary=0
WQ Write To DSS=0
WQ Use Fixed Temperature=0
Sorting and Armoring Iterations= 10
XS Update Threshold= 0.02
Bed Roughness Predictor= 0
Hydraulics Update Threshold= 0.02
Energy Slope Method= 1
Volume Change Method= 1
Sediment Retention Method= 0
XS Weighting Method= 0
Number of US Weighted Cross Sections= 1
Number of DS Weighted Cross Sections= 1
Upstream XS Weight=0
Main XS Weight=1
Downstream XS Weight=0
Number of DS XS's Weighted with US Boundary= 1
Upstream Boundary Weight= 1
Weight of XSs Associated with US Boundary= 0
Number of US XS's Weighted with DS Boundary= 1
Downstream Boundary Weight= 0.5
Weight of XSs Associated with DS Boundary= 0.5
Percentile Method= 0
Sediment Output Level= 3
Mass or Volume Output= 0
Output Increment Type= 1
Profile and TS Output Increment= 1
XS Output Flag= 0
XS Output Increment= 10
Write Gradation File= 0
Read Gradation Hotstart= 0
Write HDF5 File= 1
Write Binary Output= 1
Write DSS Sediment File= 0
SV Curve= 0
Specific Gage Flag= 0

--- WHITESRN.f01 (steady flow) ---

Flow Title=Flows
Program Version=5.07
Number of Profiles= 6
Profile Names=P100yr,P10yr,P25yr,P50yr,P500yr,P101yr
River Rch & RM=WHITESRN,Main            ,10984
    1072     497     705     883    1581    1304
River Rch & RM=WHITESRN,Main            ,7375
    1204     557     791     992    1779    1466
River Rch & RM=WHITESRN,Main            ,717
    1453     670     953    1195    2150    1768
Boundary for River Rch & Prof#=WHITESRN,Main            , 1
Up Type= 0
Dn Type= 3
Dn Slope=0.03128
Boundary for River Rch & Prof#=WHITESRN,Main            , 2
Up Type= 0
Dn Type= 3
Dn Slope=0.03128
Boundary for River Rch & Prof#=WHITESRN,Main            , 3
Up Type= 0
Dn Type= 3
Dn Slope=0.03128
Boundary for River Rch & Prof#=WHITESRN,Main            , 4
Up Type= 0
Dn Type= 3
Dn Slope=0.03128
Boundary for River Rch & Prof#=WHITESRN,Main            , 5
Up Type= 0
Dn Type= 3
Dn Slope=0.03128
Boundary for River Rch & Prof#=WHITESRN,Main            , 6
Up Type= 0
Dn Type= 3
Dn Slope=0.03128
DSS Import GetInterval= 0
DSS Import GetPeak= 0
DSS Import FillOption= 0

--- WHITESRN.g01 (geometry) ---

Geom Title=Geometry
Program Version=5.07

River Reach=WHITESRN        ,Main
Reach XY= 30
2391737.38765001672349.053564742      2391894.84672313.074000001
2392401.00099999672001.3569999932393057.06400004671888.158000022
2393274.08000004      671910.9342393471.34099999672252.534000009
2393738.39700001672594.5600000022394322.05400002672738.569000021
     2394570.516672983.306999996     2395133.352673407.141000003
     2395429.942 673587.30400002     2395735.889673886.553000003
2395933.01900002674509.3719999942396330.18200001674875.424999997
2396434.37800002675035.1120000032396465.31900001675546.284999996
     2396624.549675914.8270000222396880.05900002      676069.934
2397001.61500004676346.0150000162397067.28300002676413.578000009
2397293.72100002      676511.6032397549.62100002676738.965000004
2397611.38100001 676902.593000012397951.58600003677286.335999995
2397969.14700004677368.8419999932398198.99200004677371.172000006
2398429.43200001677454.7699999962398769.71700004677295.330000013
2399339.06700003677250.7190000122399510.59900004677111.988999993

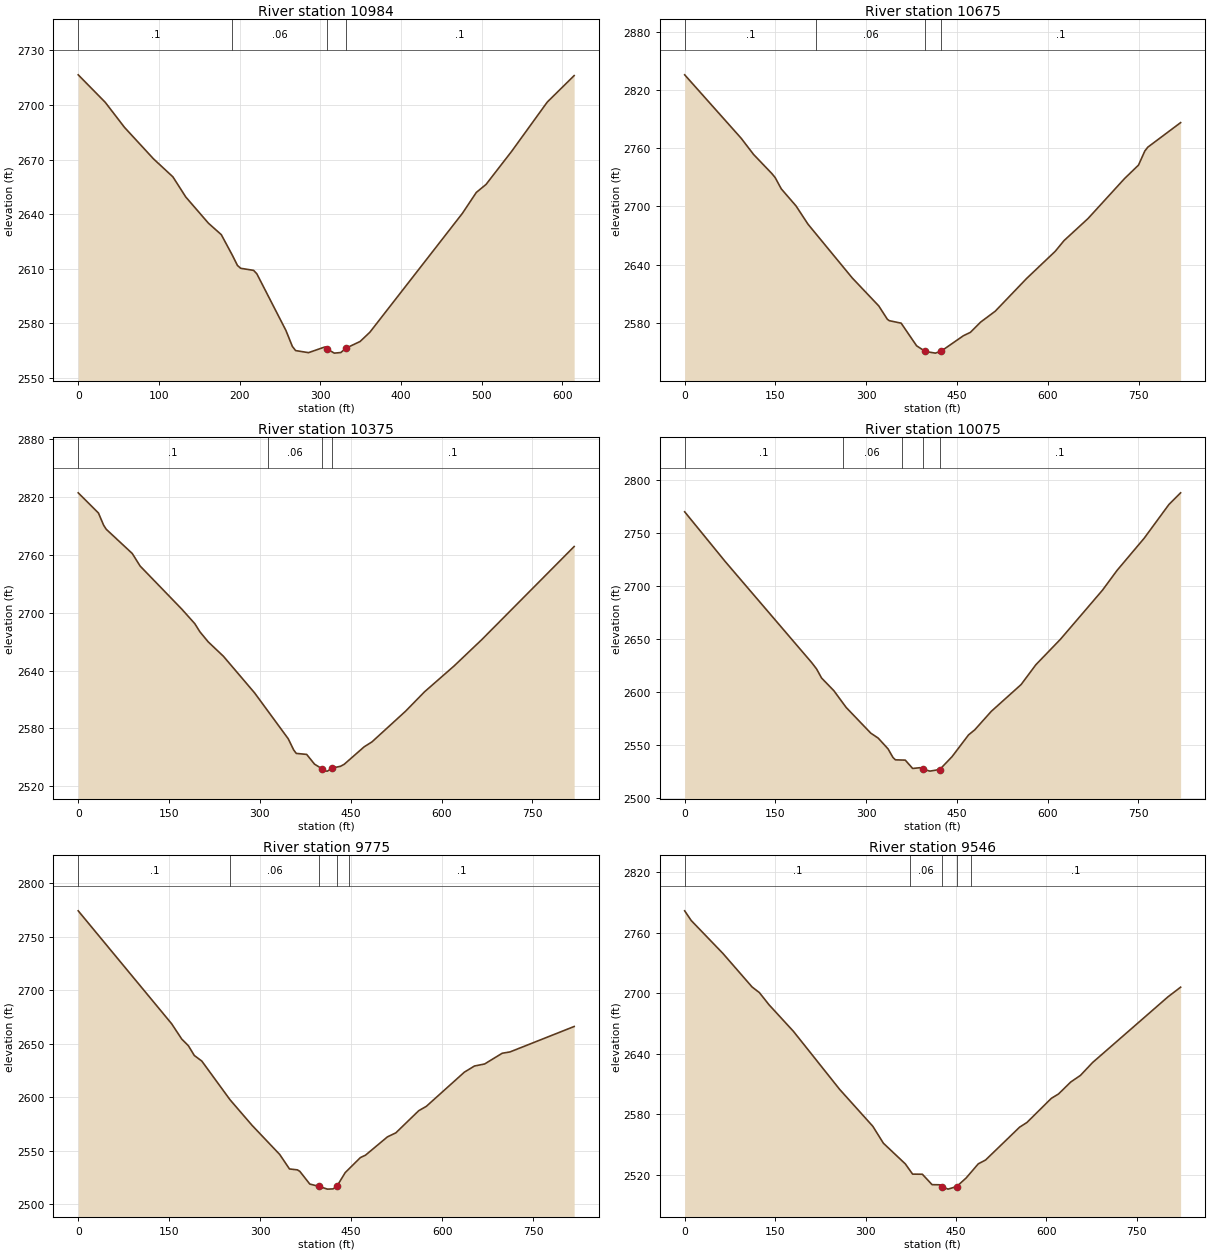
Type RM Length L Ch R = 1 ,10984   ,319.2,309.2,296.3
XS GIS Cut Line= 3
2391744.93477163672668.2763809112391737.38765001672349.053564742
2391737.46337995672053.572755963
#Sta/Elev= 30
       0  2716.6    33.4 2701.55    57.4 2687.71    93.4 2670.39   117.4 2660.52
   133.4 2649.43   161.4 2635.07   177.4 2628.75   191.1 2617.44   197.4 2611.85
   201.4 2610.27   217.4 2609.13   221.4 2607.28   257.5 2576.11   265.5 2567.32
   269.5 2565.05   285.5 2563.91   305.5    2567   308.4 2565.95   317.5 2563.65
   325.5 2563.97   332.1  2566.4   349.5 2570.06   361.5  2575.1   476.2 2640.43
   493.5 2651.96   505.5 2656.33   537.5 2674.66   581.5 2701.64   614.8 2716.17
#Mann= 4 ,-1 , 0
       0      .1       0   191.1     .06       0   308.4    .045       0
   332.1      .1       0
Bank Sta=308.4,332.1
XS Rating Curve= 0 ,0
Exp/Cntr(USF)=0,0
Exp/Cntr=0.3,0.1

Type RM Length L Ch R = 1 ,10675   ,295.9,300,303.6
XS GIS Cut Line= 3
     2392271.668      672560.195     2392018.063      672238.766
     2391777.316      671907.011
#Sta/Elev= 30
       0 2835.62    93.4 2770.24   113.8 2753.63     144 2733.94   149.4 2729.87
   159.6 2718.15   183.9 2700.64   203.8 2681.72   276.8 2626.42   320.6 2597.62
   334.8 2583.88   337.9 2582.41   357.6 2579.84   383.2 2556.49   397.5 2550.71
   414.2 2548.97   424.1 2551.17   460.4 2566.88   471.9 2570.33     489 2580.96
   513.1 2592.18   564.9 2625.87   612.2 2653.86   626.7 2664.87   666.3 2687.58
   726.7 2728.79   749.7 2742.62   760.2 2757.18   765.1 2761.11   819.3 2786.38
#Mann= 4 ,-1 , 0
       0      .1       0  217.21     .06       0   397.5    .045       0
   424.1      .1       0
Bank Sta=397.5,424.1
XS Rating Curve= 0 ,0
Exp/Cntr=0.3,0.1

Type RM Length L Ch R = 1 ,10375   ,296,300,302.9
XS GIS Cut Line= 3
     2392417.402      672458.005     2392267.469      672076.946
     2392113.384       671697.51
#Sta/Elev= 30
       0 2824.17    33.4 2803.27      42  2790.6    46.3 2786.39    89.3 2761.26
   102.2 2748.31     171 2703.66   192.5 2688.59   201.1 2680.02   214.8 2669.63
   239.8 2654.77   291.4 2616.72   346.9 2569.21   355.8 2557.73   360.1  2554.1
   377.3 2553.04   390.2 2542.98     4022538.389   407.4 2535.86   411.6 2535.72
   419.2 2538.87   433.1 2540.71   439.3 2542.83   472.2 2560.91   485.1 2566.02
   540.6 2597.82   571.8 2617.86   620.4 2644.53   666.5 2672.04     819  2768.5
#Mann= 4 ,-1 , 0
       0      .1       0  313.24     .06       0     402    .045       0
   419.2      .1       0
Bank Sta=402,419.2
XS Rating Curve= 0 ,0
Exp/Cntr=0.3,0.1

Type RM Length L Ch R = 1 ,10075   ,300.6,300,296.9
XS GIS Cut Line= 3
     2392620.554      672381.321     2392544.837      671979.072
     2392467.046       671575.95
#Sta/Elev= 30
       0 2770.29    67.6 2722.94   210.1 2627.81   218.2 2621.76   226.3 2613.35
   246.7 2601.31     267 2585.51   307.7 2561.27     320 2556.55   336.2 2546.43
   344.4 2538.25   348.4 2536.07   364.7 2535.79   376.9 2527.91   389.1 2528.63
   394.1 2527.31   405.4  2525.4   421.7 2526.93     442 2539.04   469.3 2559.62
   479.6 2564.42   506.9 2581.86   556.2 2607.16   580.6 2625.88   621.3 2649.97
   690.6  2696.2     715 2715.09   759.6  2745.3   800.5 2777.16   819.9 2788.22
#Mann= 5 ,-1 , 0
       0      .1       0   261.2     .06       0  358.79      .1       0
   394.1    .045       0   421.7      .1       0
Bank Sta=394.1,421.7
XS Rating Curve= 0 ,0
Exp/Cntr=0.3,0.1

Type RM Length L Ch R = 1 ,9775    ,222.7,229,237.3
XS GIS Cut Line= 3
2392940.29405704672319.768092622     2392834.477      671924.036
     2392716.041      671533.604
#Sta/Elev= 30
       0 2774.38   154.1 2668.73   170.7 2654.45   181.7 2648.18   191.4 2639.11
   203.8 2633.87   250.3 2597.71   286.6  2573.8   332.2 2546.55   348.3 2533.01
   361.3 2532.15   365.3 2530.78   381.8 2518.88   397.3 2516.65   410.8 2514.14
     420 2514.34   426.4 2516.72   440.1 2529.54   465.2 2543.65   473.5 2545.84
   509.8 2563.01   523.7 2566.79   561.3 2587.44   573.9 2591.55   636.6 2623.51
   653.3 2629.27     670 2631.17     699  2641.2   711.9 2642.44   817.6 2666.21
#Mann= 5 ,-1 , 0
       0      .1       0   250.8     .06       0   397.3    .045       0
   426.4     .06       0  447.15      .1       0
Bank Sta=397.3,426.4
XS Rating Curve= 0 ,0
Exp/Cntr=0.3,0.1

Type RM Length L Ch R = 1 ,9546    ,215.4,221,232.2
XS GIS Cut Line= 2
2393003.82180408672321.7233563092393110.38676668671506.205378634
#Sta/Elev= 30
       0 2781.89    10.9 2772.24    63.4 2739.63   111.8 2706.34   123.9 2700.75
     140  2688.6   180.4  2662.3     257 2604.74     312 2568.13   329.6 2551.28
   365.9 2530.81     378 2520.64   394.2 2520.52   410.3 2510.18   422.4 2510.05
   426.8 2508.14   436.8 2505.75   451.1 2508.32   466.8 2516.81   486.9 2530.83
     499 2534.62   555.5 2567.25   567.6 2571.86     608 2595.78   620.1 2600.21
   640.2 2611.99   656.4 2618.63   676.5 2631.36   801.6 2696.58   822.5 2706.13
#Mann= 5 ,-1 , 0
       0      .1       0  373.56     .06       0   426.8    .045       0
   451.1     .06       0  475.18      .1       0
Bank Sta=426.8,451.1
XS Rating Curve= 0 ,0
Exp/Cntr(USF)=0,0
Exp/Cntr=0.3,0.1

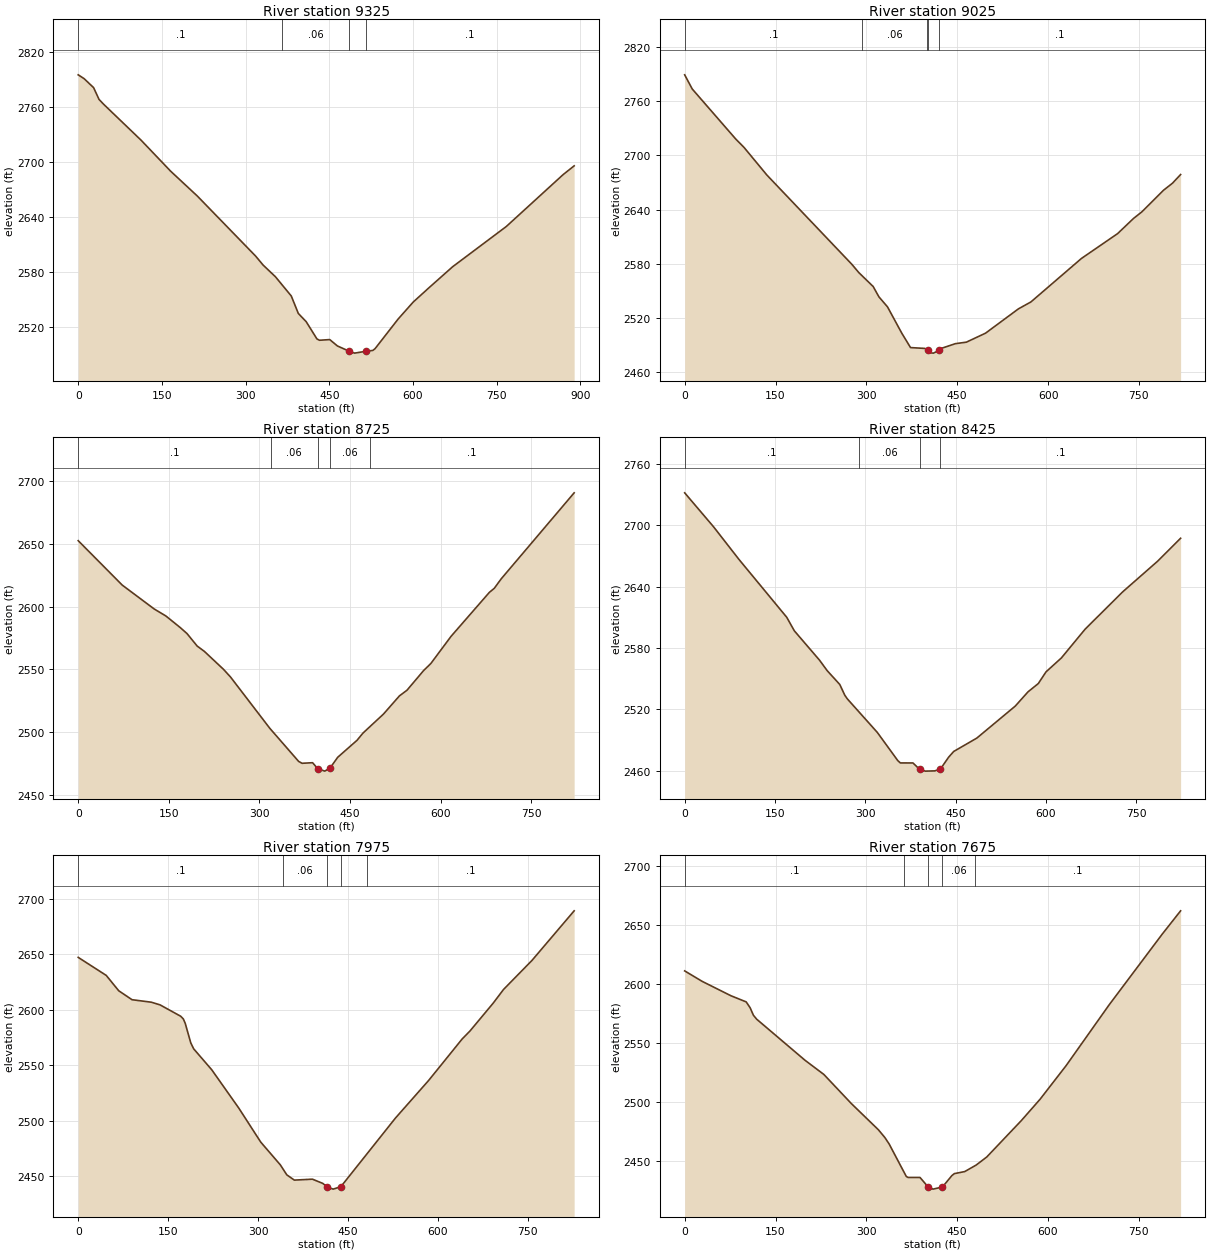
Type RM Length L Ch R = 1 ,9325    ,292.8,300,313.6
XS GIS Cut Line= 3
     2393033.556      672343.365     2393277.044      671912.873
     2393485.481      671578.019
#Sta/Elev= 30
       0  2795.5    10.5 2791.35    27.6  2781.5    37.3 2768.64    45.2 2763.55
   112.8 2723.98   165.6 2690.21   213.7 2662.88   318.2 2597.22   331.4 2587.54
   353.5 2574.76     382 2553.65   394.5 2534.67   408.7 2525.59   427.9 2506.76
   432.5 2505.31   450.9 2506.03   464.7 2499.05   485.5 2493.38   495.5 2491.23
   515.8 2493.27   528.1 2494.17   532.1 2496.09   573.5 2528.51   600.6 2547.12
   628.8 2562.72   671.2 2585.69   767.3 2629.63   869.1 2686.33     889 2695.99
#Mann= 4 ,-1 , 0
       0      .1       0  365.85     .06       0   485.5    .045       0
   515.8      .1       0
Bank Sta=485.5,515.8
XS Rating Curve= 0 ,0
Exp/Cntr=0.3,0.1

Type RM Length L Ch R = 1 ,9025    ,300.1,300,298.2
XS GIS Cut Line= 3
 2393076.1803069672392.769613809     2393421.569      672172.965
     2393783.466      671981.476
#Sta/Elev= 30
       0  2789.2    12.5 2773.52    84.3  2718.2    97.9 2708.98   135.8 2678.31
   276.1 2579.56   287.5 2570.47   311.2 2555.08   320.7 2543.64   334.9 2532.53
   358.6 2503.29   372.9 2487.52   396.6 2486.61   401.3 2484.36     406 2481.68
   410.7  2481.4   419.8 2484.38   424.3 2486.78   446.9 2491.85   465.1 2493.53
   496.7 2503.46     551 2530.35   571.6 2537.99   655.1 2586.12   714.8 2613.59
   741.1  2630.4   754.7 2637.58   790.6 2661.56   805.4 2669.35   818.8 2678.93
#Mann= 5 ,-1 , 0
       0      .1       0  292.73     .06       0  400.84      .1       0
   401.3    .045       0   419.8      .1       0
Bank Sta=401.3,419.8
XS Rating Curve= 0 ,0
Exp/Cntr=0.3,0.1

Type RM Length L Ch R = 1 ,8725    ,313.9,300,288.2
XS GIS Cut Line= 3
     2393245.416      672646.845     2393587.939      672422.414
2393925.98872637672187.442726373
#Sta/Elev= 30
       0 2652.42    72.9 2617.09   125.9 2598.07   145.1 2592.55     169 2583.29
   180.1 2578.57     197  2568.6   208.9 2564.37   240.6 2550.09   252.3 2543.93
   317.2 2503.22     365 2476.85   370.7 2475.37   388.1 2475.82   396.7 2471.05
   408.3 2469.13     4172471.584   429.7 2480.15   461.6 2493.61   471.7 2499.47
   505.5 2514.52   531.9 2528.98   544.4 2533.47   572.1  2549.2   583.9 2554.72
   617.5 2576.41   680.8  2611.3     689 2614.56   700.3    2622   821.2 2690.48
#Mann= 5 ,-1 , 0
       0      .1       0   318.9     .06       0   396.7    .045       0
     417     .06       0   483.2      .1       0
Bank Sta=396.7,417
XS Rating Curve= 0 ,0
Exp/Cntr=0.3,0.1

Type RM Length L Ch R = 1 ,8425    ,450.8,450,450.7
XS GIS Cut Line= 3
     2393683.557       673004.65      2393805.56      672615.624
2393947.78681176672224.774029666
#Sta/Elev= 30
       0 2731.85      48 2698.57    90.1  2666.7   169.5    2610   182.1 2596.76
     224 2567.97   236.6  2557.8   257.6  2544.2   265.9 2533.74   270.1 2530.14
   319.9  2497.3     354 2469.63   358.2 2467.41   379.1  2467.4   390.1 2461.16
   399.7 2459.39   415.4 2459.64   424.8 2461.48   438.3 2473.01   446.8 2478.65
   485.1  2491.7     549 2523.06   570.2 2537.02   587.3 2545.15     600 2556.52
   625.6 2570.21   665.1 2598.43   727.5 2634.96   785.5 2664.95   823.6 2687.38
#Mann= 4 ,-1 , 0
       0      .1       0  289.86     .06       0   390.1    .045       0
   424.8      .1       0
Bank Sta=390.1,424.8
XS Rating Curve= 0 ,0
Exp/Cntr=0.3,0.1

Type RM Length L Ch R = 1 ,7975    ,294.7,300,310
XS GIS Cut Line= 3
     2394089.343      673097.679     2394245.438      672707.953
     2394396.718      672329.382
#Sta/Elev= 30
       0 2647.22    46.8 2630.97    67.6 2617.14    89.8 2609.07   122.1 2606.81
   136.6 2604.41   171.1 2594.13   175.4 2591.73   178.6 2587.71   187.8  2570.2
   192.6 2564.85   222.8 2545.93   267.8 2511.49   304.7 2480.64   337.3 2460.19
     348 2451.25   360.6 2446.47   390.8 2447.32     408 2443.53   415.5  2440.4
   425.3 2438.35   438.2 2440.52   529.4 2502.45   584.7 2536.29   640.7 2573.71
   653.6 2580.82   692.5 2606.03   709.6 2618.26     757  2644.4   827.5 2689.18
#Mann= 5 ,-1 , 0
       0      .1       0  341.72     .06       0   415.5    .045       0
   438.2     .06       0  481.52      .1       0
Bank Sta=415.5,438.2
XS Rating Curve= 0 ,0
Exp/Cntr=0.3,0.1

Type RM Length L Ch R = 1 ,7675    ,302.9,300,294.7
XS GIS Cut Line= 3
     2394164.989       673157.47     2394474.377      672889.238
     2394787.567      672625.171
#Sta/Elev= 30
       0  2611.2    28.8 2602.34    76.4 2590.12   101.6 2584.89     108 2580.02
   113.5 2573.61   118.8 2570.28   198.7  2535.4   229.9 2523.33   275.3 2498.62
     320 2476.39   330.6 2469.85   337.7 2464.34     366 2436.82   368.9 2435.97
   388.7 2435.94     4022427.928     410 2426.05   425.7 2427.83   441.3 2437.52
   445.5 2439.22   462.5 2440.93   481.4 2446.46   498.9  2453.3   556.2  2484.3
   586.9 2502.26     630 2530.83   700.9 2582.29   788.9  2642.5   819.1 2662.16
#Mann= 5 ,-1 , 0
       0      .1       0     362     .06       0     402    .045       0
   425.7     .06       0  480.24      .1       0
Bank Sta=402,425.7
XS Rating Curve= 0 ,0
Exp/Cntr=0.3,0.1

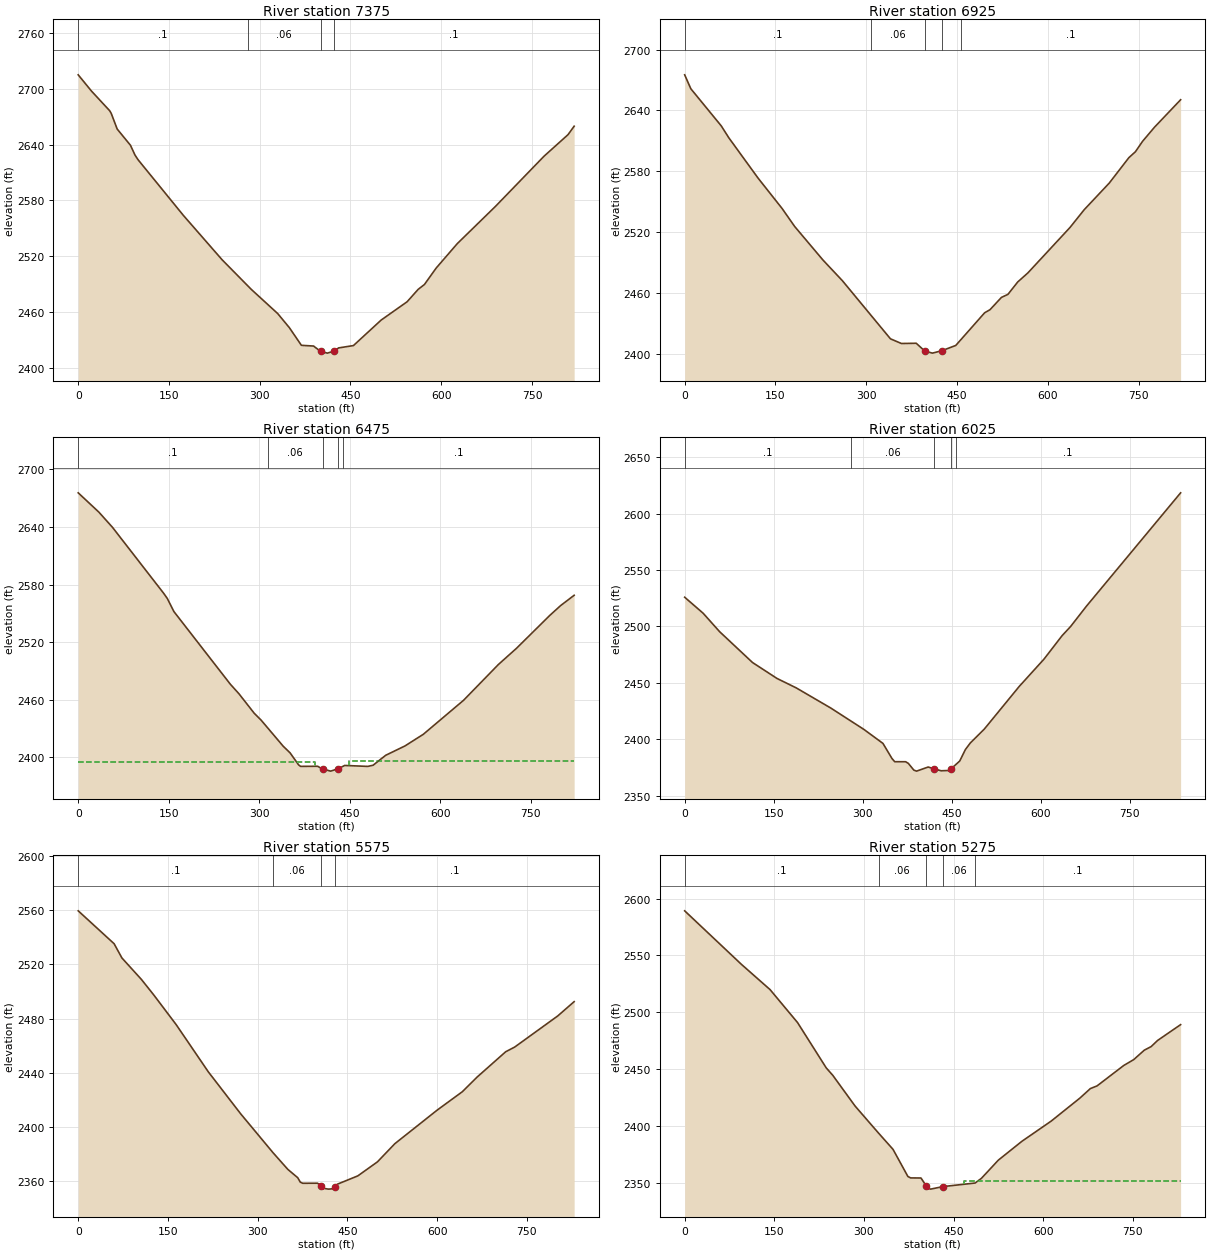
Type RM Length L Ch R = 1 ,7375    ,448,450,451.2
XS GIS Cut Line= 3
     2394464.532      673415.282     2394702.945      673081.186
     2394944.376      672750.668
#Sta/Elev= 30
       0 2714.97    21.9 2697.53      52  2676.4    54.5 2673.68    64.4 2656.73
    86.4 2639.24    93.8 2628.82    98.8 2623.83   173.9 2563.85   237.9 2516.19
   286.1 2484.39   329.7 2458.44   348.9 2443.36   368.9  2424.3     389 2423.52
   400.5 2417.81   411.9 2415.91   423.2 2418.22   430.4 2421.52   454.9 2424.03
   500.7 2451.43   543.6  2471.1   561.9 2484.44   572.2 2489.63   591.6 2507.29
   626.6 2533.62   689.6 2573.56   769.9  2627.5   809.6 2650.69   819.7 2659.75
#Mann= 4 ,-1 , 0
       0      .1       0  280.32     .06       0   400.5    .045       0
   423.2      .1       0
Bank Sta=400.5,423.2
XS Rating Curve= 0 ,0
Exp/Cntr=0.3,0.1

Type RM Length L Ch R = 1 ,6925    ,449.2,450,451.5
XS GIS Cut Line= 3
     2394800.255      673663.063     2395060.851      673347.305
     2395336.201       673043.48
#Sta/Elev= 30
       0 2675.12    10.2 2661.35    60.5 2624.67    72.9 2613.01   121.2 2573.23
     161 2543.16   181.7 2525.46   228.4 2492.37   260.5 2471.97     340 2414.54
   358.1 2409.94   382.6 2410.16   396.8 2402.41   409.4 2400.43   425.2 2402.88
   447.9 2408.01   495.6 2440.25   504.5  2443.3   523.3  2455.4   534.1 2458.44
   550.3 2470.68   567.1 2479.64   636.7 2524.49   660.2 2542.05   701.5 2568.28
   733.9 2593.35   744.7  2599.2   756.5 2609.46   776.3 2623.46   819.4 2650.52
#Mann= 5 ,-1 , 0
       0      .1       0  307.45     .06       0   396.8    .045       0
   425.2     .06       0  456.78      .1       0
Bank Sta=396.8,425.2
XS Rating Curve= 0 ,0
Exp/Cntr=0.3,0.1

Type RM Length L Ch R = 1 ,6475    ,445,450,454.9
XS GIS Cut Line= 3
     2395149.551      673894.011     2395434.906      673593.607
2395732.63761381673315.602613809
#Sta/Elev= 30
       0 2675.68    34.2  2655.6    56.8 2639.73   141.7 2570.94   147.7 2565.55
   158.5 2552.05     252 2476.37   266.2 2466.48   291.6 2446.11     303 2438.96
   339.7 2411.71   351.1 2404.78   365.2 2392.29   368.4 2390.75   396.7 2390.86
   404.8 2387.99   418.3  2385.8   430.5 2388.28   441.6 2391.71   479.8 2390.72
   488.6 2391.95   509.5 2402.31   541.4 2412.03   571.8 2424.17   638.5  2459.6
   696.3 2496.93   726.1 2513.68   781.2 2547.91   799.3 2558.24   821.7 2568.97
#Mann= 5 ,-1 , 0
       0      .1       0  314.45     .06       0   404.8    .045       0
   430.5     .06       0   438.2      .1       0
#XS Ineff= 2 , 0
          391.97 2395.49  448.16         2396.23
Permanent Ineff=
       F       F
Bank Sta=404.8,430.5
XS Rating Curve= 0 ,0
Exp/Cntr=0.3,0.1

Type RM Length L Ch R = 1 ,6025    ,445.9,450,454.5
XS GIS Cut Line= 3
     2395375.718      674123.911     2395748.537      673910.287
     2396106.785      673719.384
#Sta/Elev= 30
       0 2525.87    31.1 2511.68    58.8 2495.37   114.3 2467.99   155.6 2453.84
   187.9 2445.51   246.2 2427.62   301.9  2408.7   334.1 2396.26   349.2 2382.93
   353.9 2380.04   372.3 2380.02   376.9 2378.53   386.1  2372.6   390.7 2371.69
   410.3 2375.33   420.4 2373.63   432.2    2372   445.4 2372.27   448.6 2373.61
   463.4 2380.63     473 2390.84   481.1 2396.56     505 2409.07   563.6 2446.74
   605.3 2470.92   636.1 2491.91     650 2499.76   676.9 2517.91   835.6 2618.43
#Mann= 5 ,-1 , 0
       0      .1       0  280.37     .06       0   420.4    .045       0
   448.6     .06       0  456.91      .1       0
Bank Sta=420.4,448.6
XS Rating Curve= 0 ,0
Exp/Cntr=0.3,0.1

Type RM Length L Ch R = 1 ,5575    ,308.5,300,289.8
XS GIS Cut Line= 3
2395468.88772276674450.900802049     2395872.616       674340.08
     2396266.121      674224.272
#Sta/Elev= 30
       0 2559.42      60 2535.18    73.1 2524.66   105.7 2508.84   126.4 2497.37
   163.7 2475.59   217.6  2440.7   271.5 2409.88   325.5 2381.26   350.4 2368.89
   366.9 2362.78   371.1 2359.56   375.2 2358.67   400.1 2358.72   406.1 2356.49
   408.4 2355.12   418.1 2354.36   425.1  2354.6   429.2  2356.2   433.4 2358.04
   467.3 2364.11   500.1 2374.44   529.3 2387.87   600.2 2412.66   641.9 2426.09
   666.9    2437   714.5 2455.59   729.4    2459   801.5 2481.97   828.9  2492.5
#Mann= 4 ,-1 , 0
       0      .1       0   325.5     .06       0   406.1    .045       0
   429.2      .1       0
Bank Sta=406.1,429.2
XS Rating Curve= 0 ,0
Exp/Cntr=0.3,0.1

Type RM Length L Ch R = 1 ,5275    ,299,300,299.5
XS GIS Cut Line= 3
2395733.55833657674896.645168285     2396014.978      674593.422
     2396309.753      674299.401
#Sta/Elev= 30
       0 2589.29    95.2 2542.05   142.9 2519.93   188.9 2490.91   236.9 2451.01
     248 2444.36   285.1 2417.47   324.4 2393.62   348.7 2379.26   373.5 2355.44
   378.1 2354.12   395.5 2354.05     404 2347.28   406.8 2345.09   411.7 2344.25
   432.3 2346.49     486 2349.62   496.6 2353.73   524.9 2369.75   564.5 2386.41
   613.3 2404.12   661.4 2424.38   678.9 2432.76   690.2 2435.16   734.9 2453.15
   751.5 2458.28   769.3 2466.63   780.6 2469.71   791.5 2475.16     830 2489.08
#Mann= 5 ,-1 , 0
       0      .1       0   324.4     .06       0     404    .045       0
   432.3     .06       0     486      .1       0
#XS Ineff= 2 , 0
       0                   468.3       0    2351
Permanent Ineff=
       F       F
Bank Sta=404,432.3
XS Rating Curve= 0 ,0
Exp/Cntr=0.3,0.1

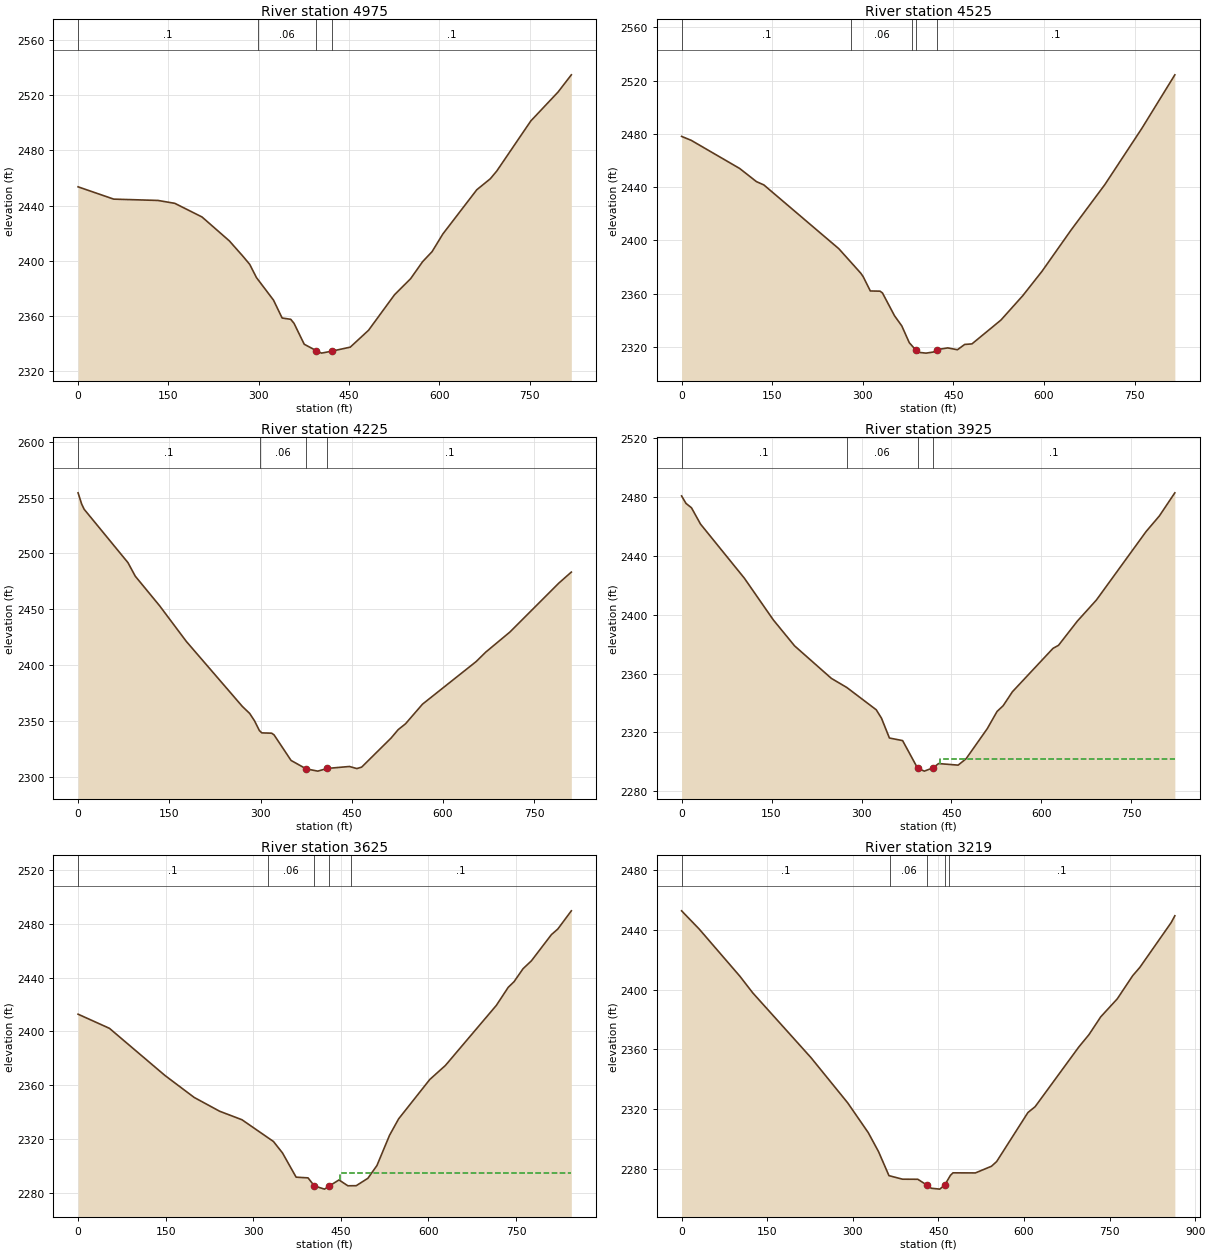
Type RM Length L Ch R = 1 ,4975    ,433.2,450,464.2
XS GIS Cut Line= 3
      2395952.79      675076.023     2396243.017      674787.125
     2396534.446      674499.446
#Sta/Elev= 30
       0 2453.57    59.2 2444.66   132.6 2443.71   160.6 2441.62   205.8 2431.74
   251.1 2414.47   273.7 2403.33     285 2397.44   296.2 2387.86   324.5 2371.55
   338.8  2358.6   353.1 2357.68   358.6 2354.73   375.5 2339.62   395.3 2335.03
   404.2 2333.19   421.2 2334.61   451.9 2337.51   482.2 2349.69   525.4 2375.43
   552.2  2387.1   572.1 2399.41   587.7 2406.61   605.8  2419.5     662 2451.44
   684.5 2459.41   695.2    2465   751.7 2501.24     797  2522.2     819 2534.64
#Mann= 4 ,-1 , 0
       0      .1       0  298.41     .06       0   395.3    .045       0
   421.2      .1       0
Bank Sta=395.3,421.2
XS Rating Curve= 0 ,0
Exp/Cntr=0.3,0.1

Type RM Length L Ch R = 1 ,4525    ,298.9,300,299.3
XS GIS Cut Line= 3
2396034.86113862675194.589475189     2396441.031      675168.601
     2396850.591      675158.842
#Sta/Elev= 30
       0 2478.07    15.9 2475.14    96.1 2454.03   123.9 2444.16   136.2 2441.68
   260.4 2393.78   296.5 2375.54   300.5 2372.95   312.5  2362.1   328.6 2361.95
   332.6  2360.6   352.6 2343.47   364.6 2335.88     377  2323.3   387.6 2317.89
   392.7 2316.04   404.7 2315.46   416.7 2316.27   423.4 2318.11   440.7 2319.38
   456.7    2318   468.7 2321.97   480.8  2322.4   528.7 2340.25   564.8 2358.51
   596.8  2376.9   644.7 2407.71   700.8 2441.92   762.1 2484.12   816.7 2524.28
#Mann= 5 ,-1 , 0
       0      .1       0  281.06     .06       0  380.84      .1       0
   387.6    .045       0   423.4      .1       0
Bank Sta=387.6,423.4
XS Rating Curve= 0 ,0
Exp/Cntr=0.3,0.1

Type RM Length L Ch R = 1 ,4225    ,309.3,300,292.7
XS GIS Cut Line= 3
2396064.79983171675481.392465479     2396463.687      675466.838
     2396875.294      675451.472
#Sta/Elev= 30
       0 2554.23     5.9 2544.17      10  2539.5      82 2491.72      94 2479.59
     134  2453.1   178.1 2421.06   270.1  2362.9   282.1 2356.65   290.1 2350.01
   298.1 2341.31   302.1 2339.22   318.2 2338.95   322.2 2337.46   350.2 2314.52
     375    2307   394.1 2304.96   409.8 2307.38   446.2 2309.12   458.3 2307.25
   466.3 2308.56   514.7 2334.62   526.3 2342.12   538.3 2347.32   566.3 2364.94
   654.4 2403.05   670.4 2411.61   710.1 2429.58   790.5 2473.39     811 2483.23
#Mann= 4 ,-1 , 0
       0      .1       0  298.39     .06       0     375    .045       0
   409.8      .1       0
Bank Sta=375,409.8
XS Rating Curve= 0 ,0
Exp/Cntr=0.3,0.1

Type RM Length L Ch R = 1 ,3925    ,309.6,300,291.5
XS GIS Cut Line= 3
2396167.79135653675921.743683385     2396535.647      675752.926
     2396914.245      675576.548
#Sta/Elev= 30
       0 2480.73     7.4 2475.63    16.5 2472.68    31.5 2461.64   104.5  2424.9
   152.9 2396.48   188.4  2378.8   249.7 2356.71   275.4 2350.53   324.5 2335.37
   333.2 2329.71   346.5 2316.16   368.5  2314.4   393.5 2295.66   404.7 2293.65
     419 2295.85   428.5 2298.79   461.1 2297.72   474.4  2302.1   509.7 2322.55
     526 2334.22   536.1  2338.1   551.6 2347.62   619.3 2377.13   628.4 2379.16
   659.7 2395.56   691.6 2409.97   774.4  2456.5   796.5 2467.09   822.4 2482.85
#Mann= 4 ,-1 , 0
       0      .1       0   275.4     .06       0   393.5    .045       0
     419      .1       0
#XS Ineff= 2 , 0
       0                   430.2       0    2302
Permanent Ineff=
       F       F
Bank Sta=393.5,419
XS Rating Curve= 0 ,0
Exp/Cntr=0.3,0.1

Type RM Length L Ch R = 1 ,3625    ,393.5,406.2,412.4
XS GIS Cut Line= 3
2396476.12911866676330.886029666     2396714.472      675983.073
     2396967.945      675644.396
#Sta/Elev= 30
       0 2412.84    53.7 2402.33   148.6 2367.33   198.8 2350.94   242.4 2340.67
   280.6 2334.36   334.6 2318.17     350  2309.7   373.4 2291.64   393.8 2291.12
   404.7 2285.11     422 2282.75   430.5 2285.17   446.8 2289.58     462 2285.24
   476.3  2285.3   496.3 2290.81   511.8  2300.3   533.4  2322.8   548.9 2334.98
   602.3 2364.28     629 2374.69   716.3  2419.4   736.6  2432.8   746.6    2437
     762 2446.65   776.3 2452.51   810.6 2472.01   821.6 2476.19   844.7  2489.7
#Mann= 5 ,-1 , 0
       0      .1       0  325.58     .06       0   404.7    .045       0
   430.5     .06       0  467.55      .1       0
#XS Ineff= 2 , 0
                          448.01          2294.5
Permanent Ineff=
       F       F
Bank Sta=404.7,430.5
XS Rating Curve= 0 ,0
Exp/Cntr=0.3,0.1

Type RM Length L Ch R = 1 ,3219    ,357.8,343.8,332.5
XS GIS Cut Line= 2
2396575.84350486676469.3766337642397344.47555448676073.821247572
#Sta/Elev= 30
       0 2452.72    30.7 2440.59   102.2 2408.94   124.7 2397.83   226.8 2354.47
   291.2 2324.18   327.2 2304.26   345.2 2291.55   363.4 2275.53   387.1 2273.16
   413.9  2273.1   430.6 2269.07   437.6  2267.1   452.5 2266.51   461.4 2269.38
   471.1 2275.73   475.6 2277.41   514.9 2277.35   543.1 2281.83   552.1 2284.95
   606.9 2317.74   619.6 2321.69     696 2361.57   713.9 2369.87   734.6 2381.83
   763.5 2393.82   790.5  2409.3     803 2414.85     858 2444.87   864.4 2449.41
#Mann= 5 ,-1 , 0
       0      .1       0  364.93     .06       0   430.6    .045       0
   461.4     .06       0  469.37      .1       0
Bank Sta=430.6,461.4
XS Rating Curve= 0 ,0
Exp/Cntr=0.3,0.1

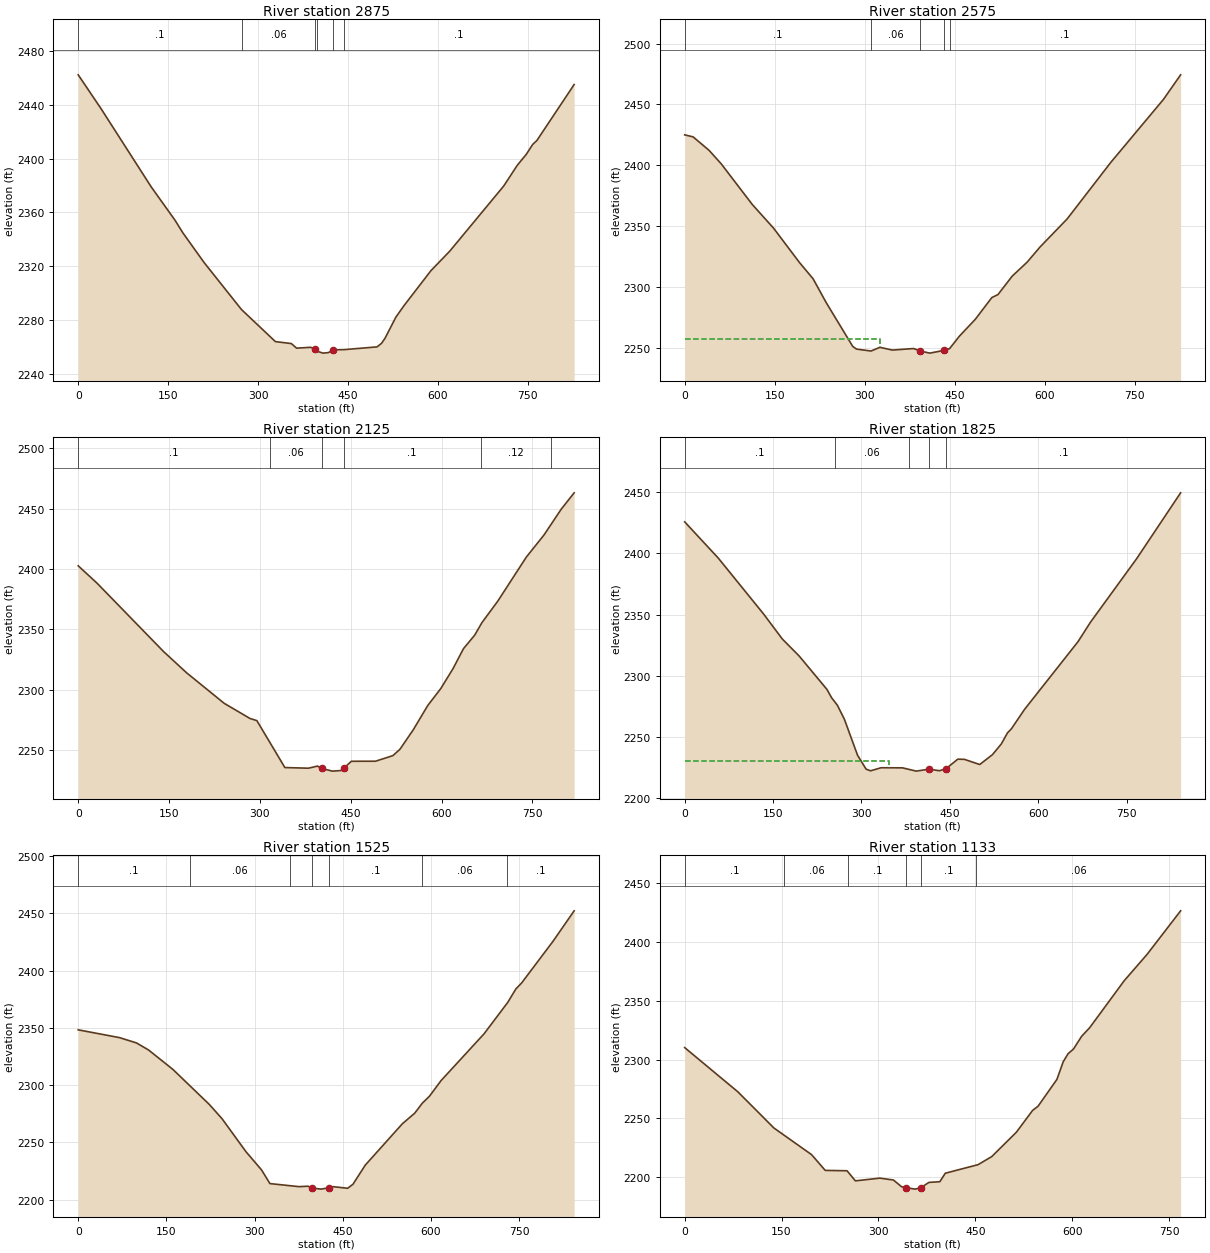
Type RM Length L Ch R = 1 ,2875    ,294.5,300,304.7
XS GIS Cut Line= 3
     2397039.149      676857.211     2397211.804      676486.225
     2397403.304      676114.498
#Sta/Elev= 30
       0  2462.1    37.9 2437.13   121.7 2379.04   161.4 2354.32   174.6 2344.89
   209.9 2322.95   272.4    2288     329 2264.22   355.5 2262.79   364.3 2259.38
   387.7    2260   395.7 2258.63   398.9    2257   408.5 2255.69   417.4 2256.08
   425.7 2258.16   443.6 2258.28   498.4 2260.31   505.9 2262.91   511.9  2266.8
   529.9 2282.37   543.4 2290.87   588.4 2316.86   619.9 2331.37   709.9 2379.69
   732.4 2394.97   747.5 2403.16   758.3 2410.58     765 2413.29   827.3 2454.91
#Mann= 6 ,-1 , 0
       0      .1       0   272.4     .06       0   395.7    .045       0
   398.9     .04       0   425.7     .06       0   443.6      .1       0
Bank Sta=395.7,425.7
XS Rating Curve= 0 ,0
Exp/Cntr=0.3,0.1

Type RM Length L Ch R = 1 ,2575    ,444.4,450,449.8
XS GIS Cut Line= 3
     2397176.351      676981.738      2397436.23      676667.195
     2397718.174      676357.873
#Sta/Elev= 30
       0 2425.03    14.1 2423.33    40.7 2412.26    60.8 2401.24   112.7 2367.75
   148.2 2348.26   191.2 2320.12     214 2306.68   236.1 2286.87   280.1 2251.07
   286.4 2248.85   310.6 2247.28   325.4 2250.33   346.1 2248.06   381.6 2249.33
     393 2247.26   408.4 2245.55   432.7 2247.85   441.4 2249.21   458.1 2259.64
   484.2 2273.28   511.9 2291.23   522.1 2293.69   545.9 2308.88   570.8 2320.38
   592.4 2332.91   637.4 2355.88   710.1 2402.35   798.1 2454.28   826.5 2474.36
#Mann= 5 ,-1 , 0
       0      .1       0   310.6     .06       0     393    .045       0
   432.7     .06       0   441.4      .1       0
#XS Ineff= 2 , 0
          326.25 2257.13
Permanent Ineff=
       F       F
Bank Sta=393,432.7
XS Rating Curve= 0 ,0
Exp/Cntr=0.3,0.1

Type RM Length L Ch R = 1 ,2125    ,302.3,300,297.7
XS GIS Cut Line= 3
     2397386.145      677270.088     2397698.805      677005.701
     2398010.927       676740.55
#Sta/Elev= 30
       0 2402.63    31.1 2388.22   141.2 2331.36   178.9 2313.91   241.1 2288.53
   283.7 2275.96     295  2274.2   341.3 2235.24   380.2 2234.71   395.2 2236.46
     4022234.498   419.9 2232.28   434.1 2232.78   438.5 2234.67   451.1 2240.46
   490.9 2240.49   519.6 2245.13   531.2 2250.33   553.3 2266.57   577.3 2286.76
   598.7 2300.74   619.3  2317.6   636.2 2333.86   654.8 2345.12   666.6  2355.4
   692.8 2373.25     740 2409.83     769 2428.06   797.8 2449.71     819 2463.17
#Mann= 6 ,-1 , 0
       0      .1       0  316.44     .06       0     402    .045       0
   438.5      .1       0  664.42     .12       0  780.45      .1       0
Bank Sta=402,438.5
XS Rating Curve= 0 ,0
Exp/Cntr=0.3,0.1

Type RM Length L Ch R = 1 ,1825    ,306.3,300,288.1
XS GIS Cut Line= 3
 2397600.9010932677544.235062619     2397896.008      677231.748
     2398170.682      676924.884
#Sta/Elev= 30
       0 2425.82    56.9 2396.25   133.9 2350.49   165.8 2329.97   194.4 2316.05
   241.5 2288.77   249.4 2281.91     259 2275.98   271.1 2264.33   293.4 2234.94
   307.9  2223.6   315.5 2222.25   333.3 2224.75   369.7 2224.66     393 2221.98
   414.5 2223.57   432.4  2222.3   443.7 2224.03   463.5 2231.77   474.8  2231.6
   500.7 2227.38   522.2 2235.42   537.2 2244.12   547.9 2253.32   554.4 2256.55
   576.8  2272.5   667.5 2327.85   688.6 2343.74   766.6 2395.44   841.6 2449.55
#Mann= 5 ,-1 , 0
       0      .1       0  254.91     .06       0  379.98      .1       0
   414.5    .045       0   443.7      .1       0
#XS Ineff= 2 , 0
          347.18    2230
Permanent Ineff=
       F       F
Bank Sta=414.5,443.7
XS Rating Curve= 0 ,0
Exp/Cntr=0.3,0.1

Type RM Length L Ch R = 1 ,1525    ,395.2,391.7,373.9
XS GIS Cut Line= 3
2397999.46193738677775.002876214     2398101.002      677376.117
     2398233.364      676964.558
#Sta/Elev= 30
       0 2348.29    70.3 2341.49    99.2 2336.86   119.8 2330.68   161.1 2313.77
     223 2283.25   244.8  2270.7   285.7  2241.8   312.1 2225.98   326.2 2214.13
   375.7 2211.46     391 2211.84   397.6 2210.31   412.9  2209.3   426.7 2210.43
   433.9 2211.43   458.5 2210.04   467.5 2213.53   488.5 2230.27   551.6 2266.34
   572.6 2275.56   585.6 2284.32   597.8 2290.43   617.4 2303.98   690.6 2344.81
   730.9 2372.24   744.8 2384.01   754.2 2388.97   807.9 2425.52   843.9 2452.13
#Mann= 7 ,-1 , 0
       0      .1       0  189.72     .06       0  360.97      .1       0
   397.6    .045       0   426.7      .1       0  585.68     .06       0
  728.97      .1       0
Bank Sta=397.6,426.7
XS Rating Curve= 0 ,0
Exp/Cntr=0.3,0.1

Type RM Length L Ch R = 1 ,1133    ,408.5,415.7,417.7
XS GIS Cut Line= 2
2398579.74198184677760.9988982632398333.28359818677033.859269862
#Sta/Elev= 30
       0 2310.28    82.5 2272.57   138.1 2241.89   196.5 2219.17   217.6 2205.79
   251.4 2205.46   264.3 2196.88   302.1 2199.19   323.2  2197.6   335.9 2191.84
   343.1    2191     357 2189.84   365.9 2191.14   378.1 2195.56     395 2196.15
   403.5 2203.39   454.1 2210.64   475.3 2217.49   513.5 2238.25   538.6 2256.79
   547.1  2260.4   576.3 2283.23     586 2298.17   593.5 2305.04     602 2309.12
   614.6 2319.92     627  2327.2   680.6 2367.28     716  2389.7   767.8 2426.67
#Mann= 6 ,-1 , 0
       0      .1       0  154.53     .06       0  253.54      .1       0
   343.1    .045       0   365.9      .1       0  451.56     .06       0
Bank Sta=343.1,365.9
XS Rating Curve= 0 ,0
Exp/Cntr(USF)=0,0
Exp/Cntr=0.3,0.1