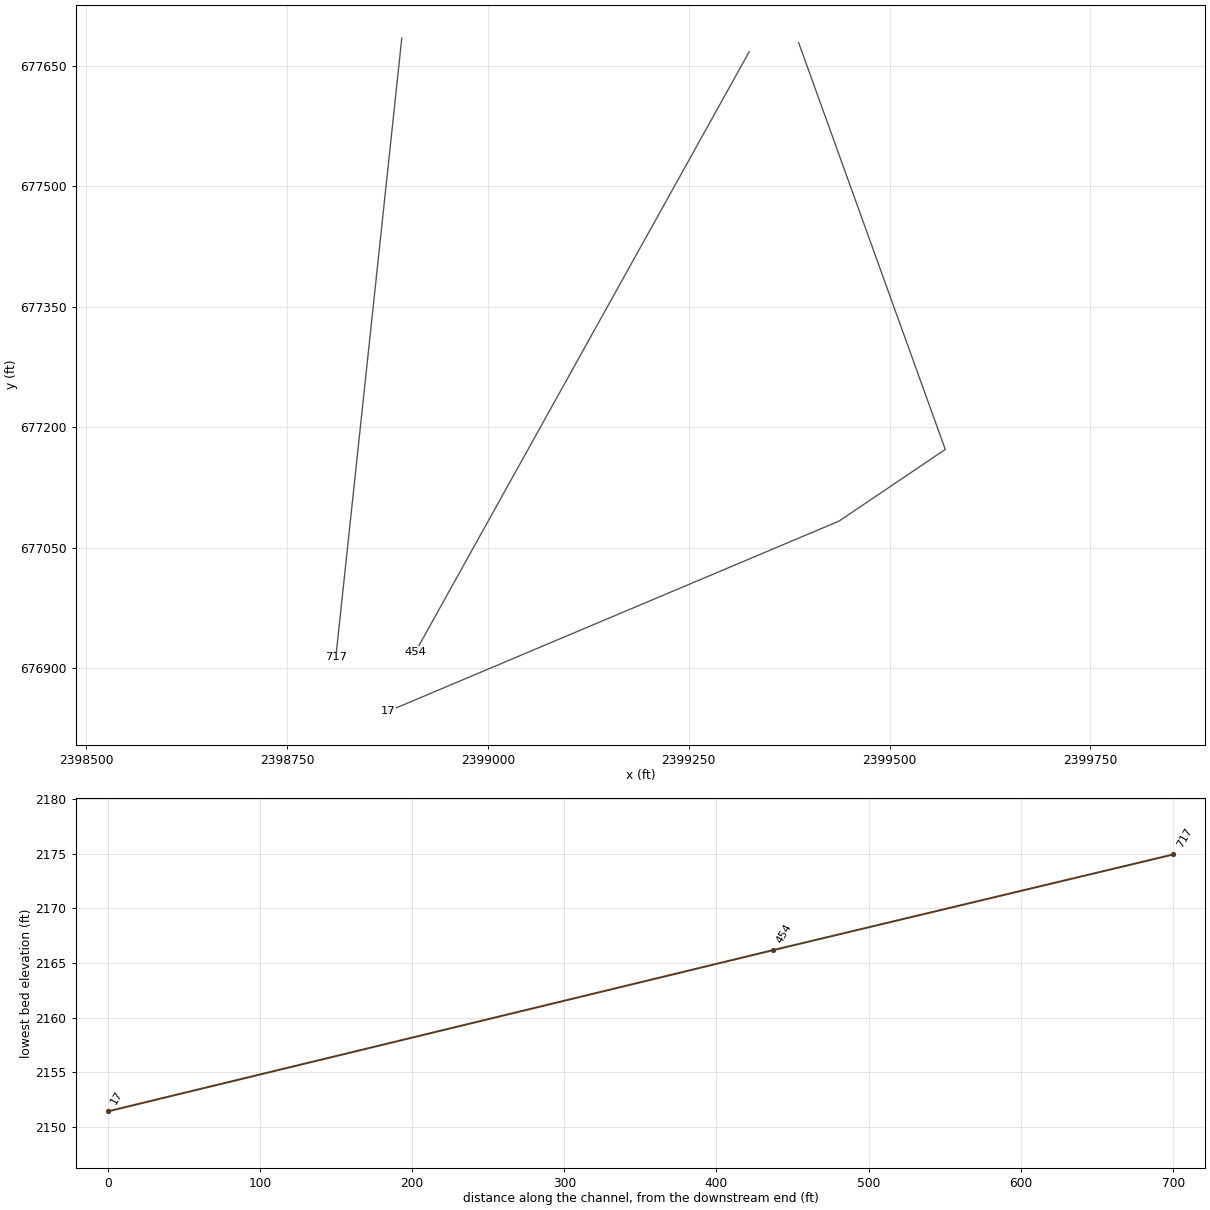
HEC-RAS study WHITESRN.prj: WHITESRN

--- WHITESRN.g01 (geometry) --- (continued)

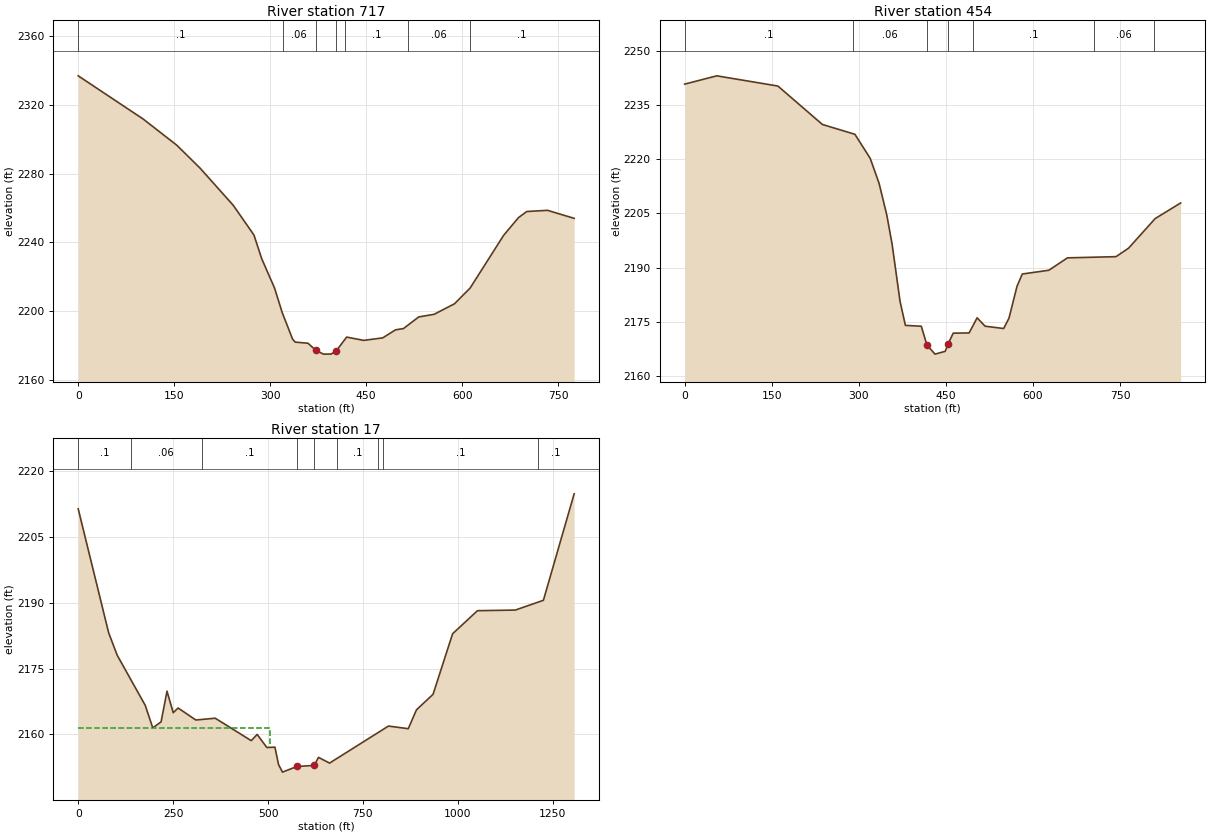
Type RM Length L Ch R = 1 ,717     ,272.4,263.3,254
XS GIS Cut Line= 2
2398892.62177387677684.0898991052398810.46897932676913.251975728
#Sta/Elev= 30
       0 2336.95   101.8 2311.73   154.1 2296.56   190.3 2283.29   242.4 2261.56
   274.7 2244.29   286.8 2230.53   306.9 2213.42   318.9 2199.11   335.1 2183.67
   339.1 2181.95   359.2 2181.29   371.3 2177.19   383.4 2174.95   395.5    2175
   403.5 2176.92   419.6 2184.87   446.3 2182.95   475.9  2184.4     496 2189.09
   508.4 2189.82   532.2  2196.6   556.3 2198.13   588.1 2204.24   612.6 2213.41
   664.9 2244.05   688.1 2254.38   701.1 2257.96   733.5 2258.66   775.2 2253.99
#Mann= 7 ,-1 , 0
       0      .1       0  319.73     .06       0   371.3    .045       0
   403.5     .06       0  417.38      .1       0  515.03     .06       0
  612.69      .1       0
Bank Sta=371.3,403.5
XS Rating Curve= 0 ,0
Exp/Cntr(USF)=0,0
Exp/Cntr=0.3,0.1

Type RM Length L Ch R = 1 ,454     ,461.2,436.9,435.2
XS GIS Cut Line= 2
2399325.19416476677667.2117350972398909.79118099676920.505758136
#Sta/Elev= 30
       0 2240.72    55.3 2243.01   160.6 2240.19   237.3 2229.58   293.3 2226.87
   319.7 2220.22     335  2213.3   348.2 2204.62   357.4 2196.53   371.1 2180.72
   380.3 2174.11   407.7 2173.87   417.5 2168.63   431.4 2166.17   448.9 2166.94
   453.5 2168.88   462.7 2171.96   490.1 2172.02   503.9  2176.2   517.6 2173.88
   549.6 2173.24   558.8 2176.11   572.6  2184.9   581.7 2188.29   627.5 2189.33
   659.5 2192.75   743.2 2193.08   764.8 2195.42   810.6 2203.59   854.5  2207.9
#Mann= 7 ,-1 , 0
       0      .1       0  289.48     .06       0   417.5    .045       0
   453.5     .06       0  497.42      .1       0  705.35     .06       0
  809.31      .1       0
Bank Sta=417.5,453.5
XS Rating Curve= 0 ,0
Exp/Cntr(USF)=0,0
Exp/Cntr=0.3,0.1

Type RM Length L Ch R = 1 ,17      ,,,
XS GIS Cut Line= 4
2399386.84723226677678.3751028912399569.34583359677172.210719084
2399437.02756869677082.9905000922398876.13215256676846.500472559
#Sta/Elev= 30
       0 2211.46    80.2 2183.19   102.7 2178.07   176.6 2166.63   196.4 2161.49
   218.3 2162.87   233.9 2169.86   250.3 2164.95   263.1 2166.03   309.9 2163.29
   360.9  2163.7   455.8 2158.58   471.4    2160   496.9 2157.02   518.2 2157.09
   527.7 2153.13   538.1  2151.4   576.2 2152.69   621.6 2152.93   632.9 2154.77
   662.1 2153.46   817.3 2161.91   869.4 2161.31   891.1 2165.62   934.7 2169.15
   986.2 2182.96  1051.7 2188.23  1151.4 2188.37  1225.4  2190.6  1306.4 2214.89
#Mann= 9 ,-1 , 0
       0      .1       0   138.4     .06       0  325.04      .1       0
   576.2    .045       0   621.6     .06       0  682.57      .1       0
  789.64     .06       0  802.89      .1       0 1210.42      .1       0
#XS Ineff= 2 , 0
          504.13 2161.38
Permanent Ineff=
       F       F
Bank Sta=576.2,621.6
XS Rating Curve= 0 ,0
Exp/Cntr(USF)=0,0
Exp/Cntr=0.3,0.1
LCMann Table=0

Chan Stop Cuts=-1
Use User Specified Reach Order=0
Composite Channel Slope=5